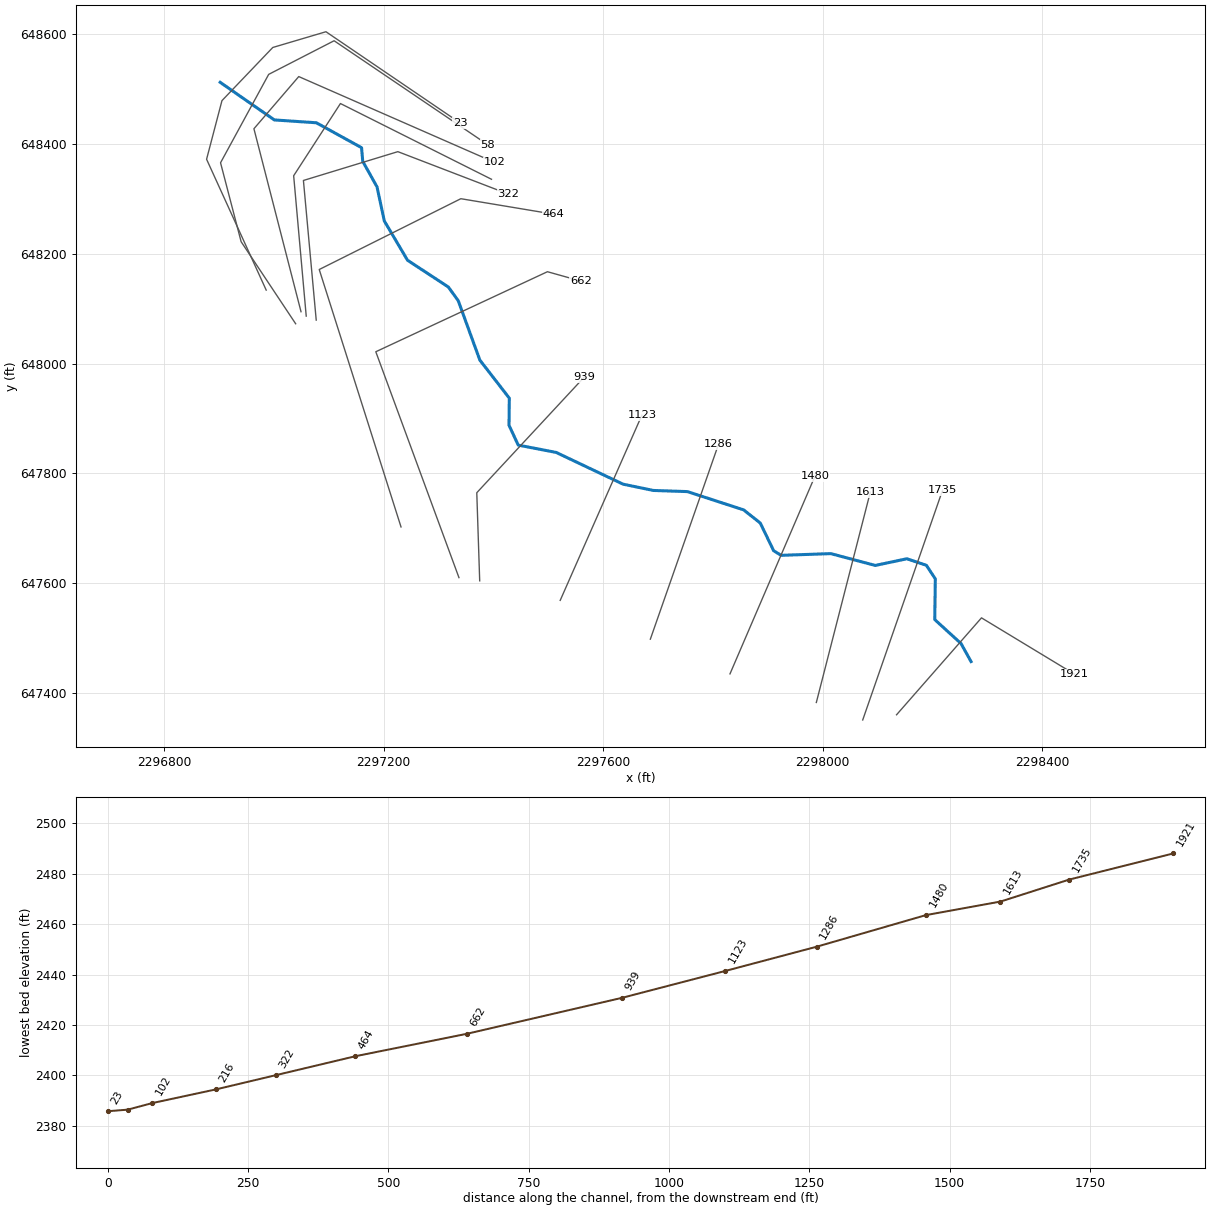
--- KNGHTSBR.prj (project) ---

Proj Title=KNGHTSBR
Current Plan=p01
Default Exp/Contr=0,0
English Units
Geom File=g01
Flow File=f01
Plan File=p01
Background Map Layer=Inundation Boundary (P100yr Value_0)
BEGIN DESCRIPTION:
----------MODEL BY WOOD PLC 2022----------
AFH study
Randolph County, WV
HEC-RAS Version: RAS 6.2
Vertical Datum: NAVD88
Projection: NAD 1983 StatePlane West Virginia S FIPS 4702 (US Feet)
Terrain: 1-meter LIDAR (FEMA Region III 3DEP collected 2016-2018)
Land Use: 2019 NLCD
Hydrologic Method:
WV SIR2010-5033 regression equations
Additional Model Notes:
None
END DESCRIPTION:
DSS Export Rating Curves= 0
DSS Export Rating Curve Sorted= 0
DSS Export Volume Flow Curves= 0
DXF OffsetX= 0
DXF OffsetY= 0
DXF ScaleX= 0
DXF ScaleY= 0

--- KNGHTSBR.p01 (plan) ---

Plan Title=Floodplain
Program Version=6.20
Short Identifier=Floodplain
Geom File=g01
Flow File=f01
Subcritical Flow
K Sum by GR= 0
Std Step Tol= 0.01
Critical Tol= 0.01
Num of Std Step Trials= 20
Max Error Tol= 0.3
Flow Tol Ratio= 0.001
Split Flow NTrial= 30
Split Flow Tol= 0.02
Split Flow Ratio= 0.02
Log Output Level= 0
Friction Slope Method= 1
Unsteady Friction Slope Method= 2
Unsteady Bridges Friction Slope Method= 1
Parabolic Critical Depth
Global Vel Dist= 0 , 0 , 0
Global Log Level= 0
CheckData=False
Encroach Param=-1 ,0,0, 0
Mapping Interval=1HOUR
Computation Time Step Use Courant=        0
Computation Time Step Use Time Series=    0
Computation Time Step Count To Double=0
Computation Time Step Max Doubling=0
Computation Time Step Max Halving=0
Computation Time Step Residence Courant=0
Run HTab= 0
Run UNet= 0
Run Sediment= 0
Run PostProcess= 0
Run WQNet= 0
Run RASMapper=-1
UNET Theta= 0
UNET Theta Warmup= 0
UNET ZTol= 0
UNET ZSATol= 0
UNET MxIter= 0
UNET Max Iter WO Improvement= 0
UNET MaxInSteps= 0
UNET DtIC= 0
UNET DtMin= 0
UNET MaxCRTS= 0
UNET WFStab= 0
UNET SFStab= 0
UNET WFX= 1
UNET SFX= 1
UNET Gravity=32.174
UNET 1D Methodology=Finite Difference
UNET DSS MLevel= 1
UNET Pardiso=0
UNET DZMax Abort= 0
UNET Use Existing IB Tables= 0
UNET Froude Reduction=False
UNET Froude Limit= 0
UNET Froude Power= 0
UNET D1 Cores= 0
UNET WindReference=Eulerian
UNET WindDragFormulation=Hsu (1988)
UNET D2 Coriolis=0
UNET D2 Cores= 0
UNET D2 Theta= 1
UNET D2 Theta Warmup= 1
UNET D2 Z Tol= 0.01
UNET D2 Volume Tol= 0.01
UNET D2 Max Iterations= 20
UNET D2 Equation= 0
UNET D2 RampUpFraction=0.1
UNET D2 TimeSlices= 1
UNET D2 Turbulence Formulation=Non-Conservative (original)
UNET D2 Eddy Viscosity=0.3
UNET D2 Transverse Eddy Viscosity=0.1
UNET D2 Smagorinsky Mixing=0
UNET D2 BCVolumeCheck=0
UNET D2 Cores=0
UNET D2 SolverType=PARDISO (Direct)
UNET D2 Minimum Iterations= 2147483647
UNET D2 Maximum Iterations= 2147483647
UNET D2 Restart Number= 10
UNET D2 Relaxation Coeff=1.3
UNET D2 SOR Precondition Iterations= 10
UNET D2 ILUT Maximum Fill= 8
UNET D2 ILUT Tolerance=1E-08
UNET D1D2 MaxIter= 0
UNET D1D2 ZTol=0.01
UNET D1D2 QTol=0.1
UNET D1D2 MinQTol=1
Write IC File= 0
Write IC File at Fixed DateTime=0
Write IC File at Sim End=0
Echo Input=False
Echo Parameters=False
Echo Output=False
Write Detailed= 0
HDF Write Warmup=0
HDF Write Time Slices=0
HDF Flush=0
HDF Compression= 1
HDF Chunk Size= 1
HDF Spatial Parts= 1
HDF Use Max Rows=0
HDF Fixed Rows= 1
Calibration Method= 0
Calibration Iterations= 20
Calibration Max Change=0.05
Calibration Tolerance=0.2
Calibration Maximum=1.5
Calibration Minimum=0.5
Calibration Optimization Method= 1
WQ AD Non Conservative
WQ ULTIMATE=-1
WQ Max Comp Step=1HOUR
WQ Output Interval=15MIN
WQ Output Selected Increments= 0
WQ Output face flow=0
WQ Output face velocity=0
WQ Output face area=0
WQ Output face dispersion=0
WQ Output cell volume=0
WQ Output cell surface area=0
WQ Output cell continuity=0
WQ Output cumulative cell continuity=0
WQ Output face conc=0
WQ Output face dconc_dx=0
WQ Output face courant=0
WQ Output face peclet=0
WQ Output face adv mass=0
WQ Output face disp mass=0
WQ Output cell mass=0
WQ Output cell source sink temp=0
WQ Output nsm pathways=0
WQ Output nsm derived pathways=0
WQ Create Restart=0
WQ Fixed Restart=0
WQ System Summary=0
WQ Write To DSS=0
Sorting and Armoring Iterations= 10
XS Update Threshold= 0.02
Bed Roughness Predictor= 0
Hydraulics Update Threshold= 0.02
Energy Slope Method= 1
Volume Change Method= 1
Sediment Retention Method= 0
Sediment TS Multiplier= 1
Warm Up Method= 0
XS Weighting Method= 0
Number of US Weighted Cross Sections= 1
Number of DS Weighted Cross Sections= 1
Upstream XS Weight=0
Main XS Weight=1
Downstream XS Weight=0
Number of DS XS's Weighted with US Boundary= 1
Upstream Boundary Weight= 1
Weight of XSs Associated with US Boundary= 0
Number of US XS's Weighted with DS Boundary= 1
Downstream Boundary Weight= 0.5
Weight of XSs Associated with DS Boundary= 0.5
Percentile Method= 0
Sediment Output Level= 3
Mass or Volume Output= 0
Output Increment Type= 1
Profile and TS Output Increment= 1
Transport Output Increment 1
XS Output Flag= 0
XS Output Increment= 10
Read HDF5 Sediment Hotstart= 0
Sediment Hotstart Type= 0
Write Gradation File= 0
Read Gradation Hotstart= 0
Write HDF5 File= 1
Write Binary Output= 1
Write DSS Sediment File= 0
DSS Sediment Output Type= 1
SV Curve= 0
Specific Gage Flag= 0
Subcell Erosion Methods= 0
Subcell Deposition Methods= 0
Advection Scheme= 1
Matrix Solver= 0
Implicit Weighting Factor= 1
Maximum Outer Loop Convergence Iterations= 5
Convergence Maximum Absolute= 0.001
Convergence RMSE= 0.0001
Grain Fractions Max Abs Error= 0.001
Max Subgrid Regions= 1
Max Subgrid Length Scale= 3.402823E+38
Initial Layer Thickness= 3.402823E+38
Min Layer Thickness= 3.402823E+38
Max Layer Thickness= 3.402823E+38
Number of Layers= 5

--- KNGHTSBR.f01 (steady flow) ---

Flow Title=Flow
Program Version=6.20
Number of Profiles= 1
Profile Names=P100yr
River Rch & RM=KNGHTSBR,Main,1921
     314
Boundary for River Rch & Prof#=KNGHTSBR,Main            , 1
Up Type= 0
Dn Type= 3
Dn Slope=0.01775
DSS Import GetInterval= 0
DSS Import GetPeak= 0
DSS Import FillOption= 0

--- KNGHTSBR.g01 (geometry) ---

Geom Title=Geometry
Program Version=6.20

River Reach=KNGHTSBR        ,Main
Reach XY= 30
2298270.40683005647457.1858341932298252.12729873647490.098056418
2298204.28516401647533.6875569372298205.25299999647607.961999998
2298188.96600004647632.6949999932298153.45000002647644.591000006
2298095.82600003647632.4370000062298014.90800001647653.966000006
2297924.28300001647650.841000006     2297910.741647659.175000012
2297886.26199998647709.6950000082297856.05400001647733.653999999
      2297753.45647766.9870000032297691.47000003647769.069999993
2297636.26200001647780.5290000142297514.38700002647838.341000006
2297445.24500003647851.693000004      2297428.45647887.820000008
2297428.97000001 647937.299000012297375.32400002648006.569999993
2297335.91500002648114.817000017     2297317.859648139.817000002
2297243.46699999648188.6020000132297201.18900004648260.223000005
2297187.91100003 648322.282000022297161.88918529648368.796676742
2297159.70800005648393.7270000132297077.30044564 648439.10384791
2297000.84599999648444.2440000032296902.11619797648512.777243944

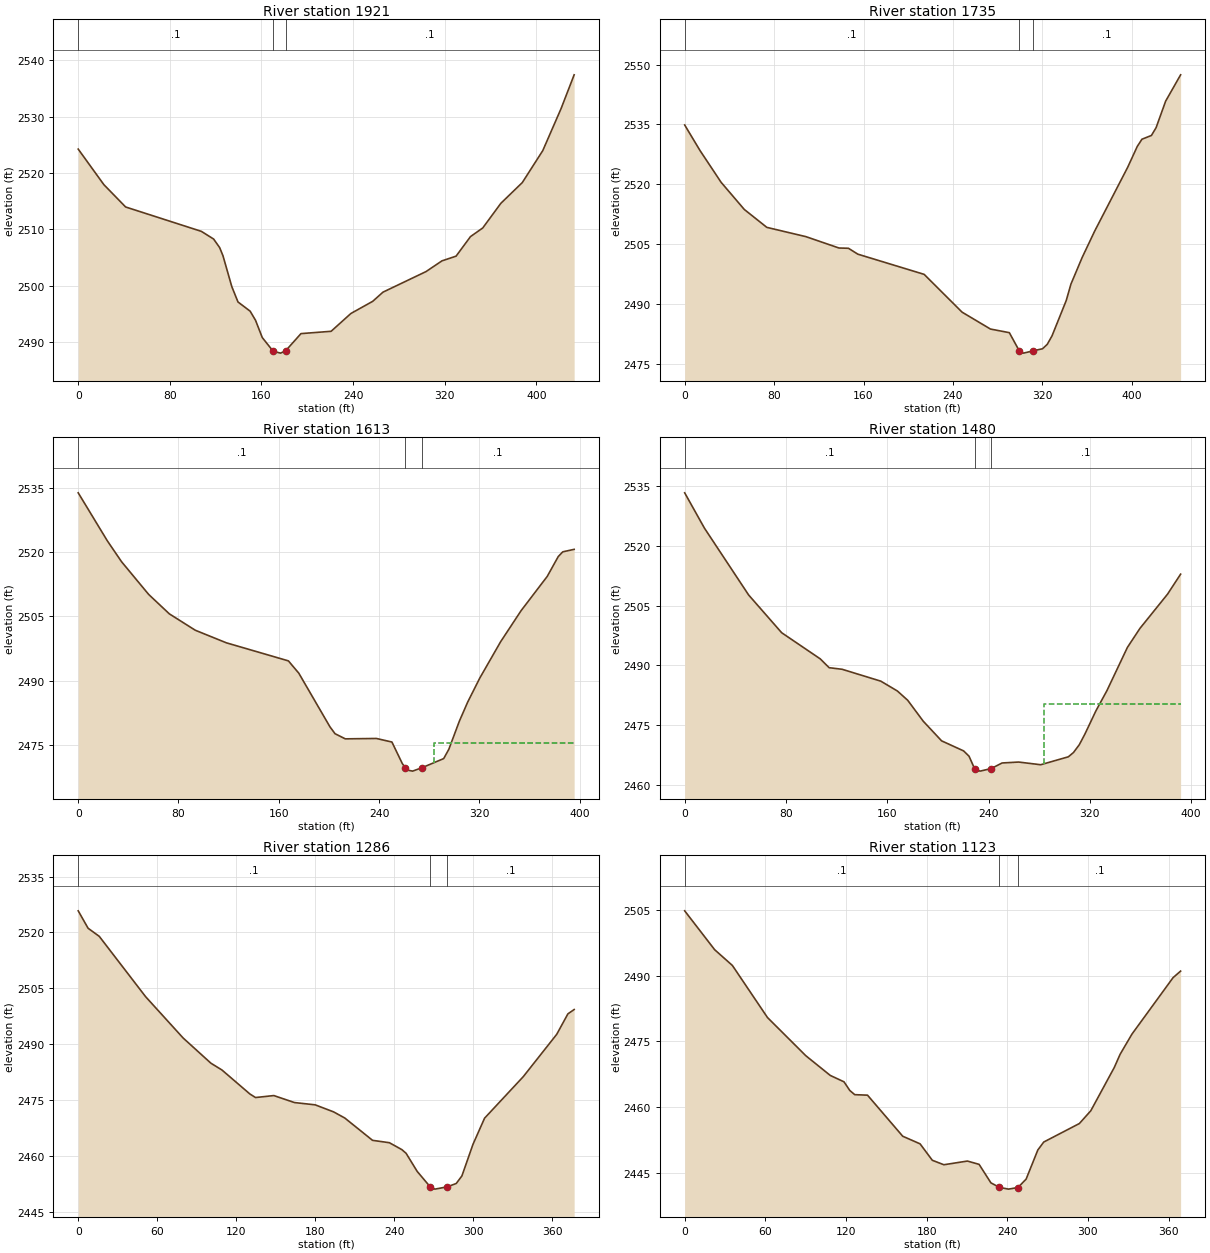
Type RM Length L Ch R = 1 ,1921    ,181.4,185.9,186.8
XS GIS Cut Line= 3
2298134.63764746647360.2970291422298289.41758485647536.924874719
2298458.91163656647434.282232583
#Sta/Elev= 30
       0 2524.23    22.4 2517.93    41.4 2513.97   107.5 2509.65   118.2 2508.29
   123.5 2506.77   126.4 2505.32   134.1 2499.85   139.5 2497.13   150.1  2495.5
   154.8 2493.89   160.7 2490.82170.26132488.383   176.7 2488.06181.24082488.505
   194.5 2491.52   220.8 2491.93   238.1 2495.09   257.1 2497.24   266.1 2498.87
   303.7 2502.52   317.6 2504.42   329.9 2505.25   342.5 2508.72   353.2 2510.25
     369 2514.62   387.7 2518.29   405.6 2523.96   421.6 2531.42     433  2537.4
#Mann= 3 ,-1,0
       0      .1       0170.2613    .045       0181.2408      .1       0
Bank Sta=170.2613,181.2408
XS Rating Curve= 0 ,0
Exp/Cntr(USF)=0,0
Exp/Cntr=0.3,0.1

Type RM Length L Ch R = 1 ,1735    ,121.5,122.3,122.1
XS GIS Cut Line= 2
2298072.98508318647350.8242864682298218.55275174647769.815070722
#Sta/Elev= 30
       0 2534.87    13.8 2528.42    32.6 2520.49    53.3 2513.69    73.5 2509.19
   108.4 2506.87     138 2504.02   146.5 2503.95   154.9 2502.47   214.2 2497.41
   248.1 2487.94   273.5  2483.7   290.4 2482.79  299.37 2478.19   303.1 2477.66
   311.6 2478.22   320.1 2478.76   324.3 2479.86   328.6    2482   341.3 2490.86
   345.5 2494.97   355.5 2501.62   366.7 2508.24   396.3 2524.28   404.8 2529.47
     409 2531.29   417.5 2532.24   421.7 2534.21   430.2 2540.84   443.6 2547.44
#Mann= 3 ,-1,0
       0      .1       0  299.37    .045       0   311.6      .1       0
Bank Sta=299.37,311.6
XS Rating Curve= 0 ,0
Exp/Cntr(USF)=0,0
Exp/Cntr=0.3,0.1

Type RM Length L Ch R = 1 ,1613    ,133.5,132.9,131.7
XS GIS Cut Line= 2
2297988.46397852647382.7190429452298086.80614432647765.987699944
#Sta/Elev= 30
       0 2533.79    23.2 2522.62    34.6 2517.73    56.2 2510.12    72.7 2505.59
    93.4 2501.77   118.2 2498.84   167.7 2494.63     176 2491.76   200.8 2479.29
   204.9 2477.66   213.1 2476.46   237.9 2476.55   250.3 2475.72   258.6 2470.69
  261.01 2469.76   262.7 2469.18   266.8 2468.94   274.5 2469.76   291.6 2471.86
   295.7 2474.03   304.1 2480.58   310.7    2485   320.4 2490.63     337 2499.08
   353.4 2506.35   374.2 2514.31     383 2518.94   386.6 2520.04395.6843 2520.62
#Mann= 3 ,-1,0
       0      .1       0  261.01    .045       0   274.5      .1       0
#XS Ineff= 2 , 0
                          283.55         2475.58
Permanent Ineff=
       F       F
Bank Sta=261.01,274.5
XS Rating Curve= 0 ,0
Exp/Cntr(USF)=0,0
Exp/Cntr=0.3,0.1

Type RM Length L Ch R = 1 ,1480    ,192.3,194.5,193.5
XS GIS Cut Line= 2
2297831.11651323647434.8138118582297985.80608215647794.692980774
#Sta/Elev= 30
       0  2533.2    15.6 2524.37    50.5 2507.65    76.6  2498.2   107.1 2491.65
   114.1 2489.45   124.4 2489.05   154.9 2486.08     168 2483.62   176.2 2481.28
   188.4 2476.07   202.9 2471.15   220.3 2468.63   224.6  2467.3     229 2464.16
   233.3 2463.57     242  2464.2   250.7 2465.61   263.8 2465.84   281.2 2465.17
     303 2467.15   307.1 2468.23   311.7 2470.19   316.1 2472.84   324.8 2478.65
   333.5 2483.71   349.7 2494.54   359.6 2499.29   381.4 2507.86   391.7 2512.85
#Mann= 3 ,-1,0
       0      .1       0     229    .045       0     242      .1       0
#XS Ineff= 2 , 0
                          283.42         2480.27
Permanent Ineff=
       F       F
Bank Sta=229,242
XS Rating Curve= 0 ,0
Exp/Cntr(USF)=0,0
Exp/Cntr=0.3,0.1

Type RM Length L Ch R = 1 ,1286    ,162.5,163.1,161.3
XS GIS Cut Line= 2
2297685.99537126647498.0717455372297810.38492152647853.698280256
#Sta/Elev= 30
       0 2525.81     7.5 2521.13      16 2518.95    51.2 2502.74    79.7 2491.64
   100.8 2484.87   109.2 2483.04   130.4  2476.6   134.7 2475.64   148.6 2476.17
   164.3 2474.29     180 2473.68     194 2471.79   202.5 2470.14   223.6 2464.14
   236.4  2463.5   245.9 2461.64   249.1 2460.65   257.5  2455.8   267.4 2451.64
     271 2451.03   280.4 2451.65   287.2 2452.55   291.5 2454.59   299.9 2463.07
   308.7 2470.09   338.1 2481.25   363.5 2492.62     372 2498.12376.7532 2499.29
#Mann= 3 ,-1,0
       0      .1       0   267.4    .045       0   280.4      .1       0
Bank Sta=267.4,280.4
XS Rating Curve= 0 ,0
Exp/Cntr(USF)=0,0
Exp/Cntr=0.3,0.1

Type RM Length L Ch R = 1 ,1123    ,185.4,183.2,180.2
XS GIS Cut Line= 2
2297521.73737541647568.771789061 2297670.5795723647906.324628444
#Sta/Elev= 30
       0 2504.74    22.3 2495.89    35.5  2492.3    61.6 2480.45    90.1 2471.76
   108.3 2467.27   118.5 2465.82   122.8 2463.86   126.5 2462.89     136 2462.78
   162.2 2453.43   175.1  2451.7   184.2 2447.96   192.8 2446.94   210.3 2447.78
     219 2447.03   227.8 2442.82   234.1 2441.79   240.9 2441.39   247.9 2441.76
     254 2443.67   262.7  2450.3   267.1 2452.11   293.6 2456.32   302.1 2459.23
   319.6  2469.1   323.9 2472.08   332.7 2476.67   363.3 2489.53368.9118 2491.02
#Mann= 3 ,-1,0
       0      .1       0   234.1    .045       0   247.9      .1       0
Bank Sta=234.1,247.9
XS Rating Curve= 0 ,0
Exp/Cntr(USF)=0,0
Exp/Cntr=0.3,0.1

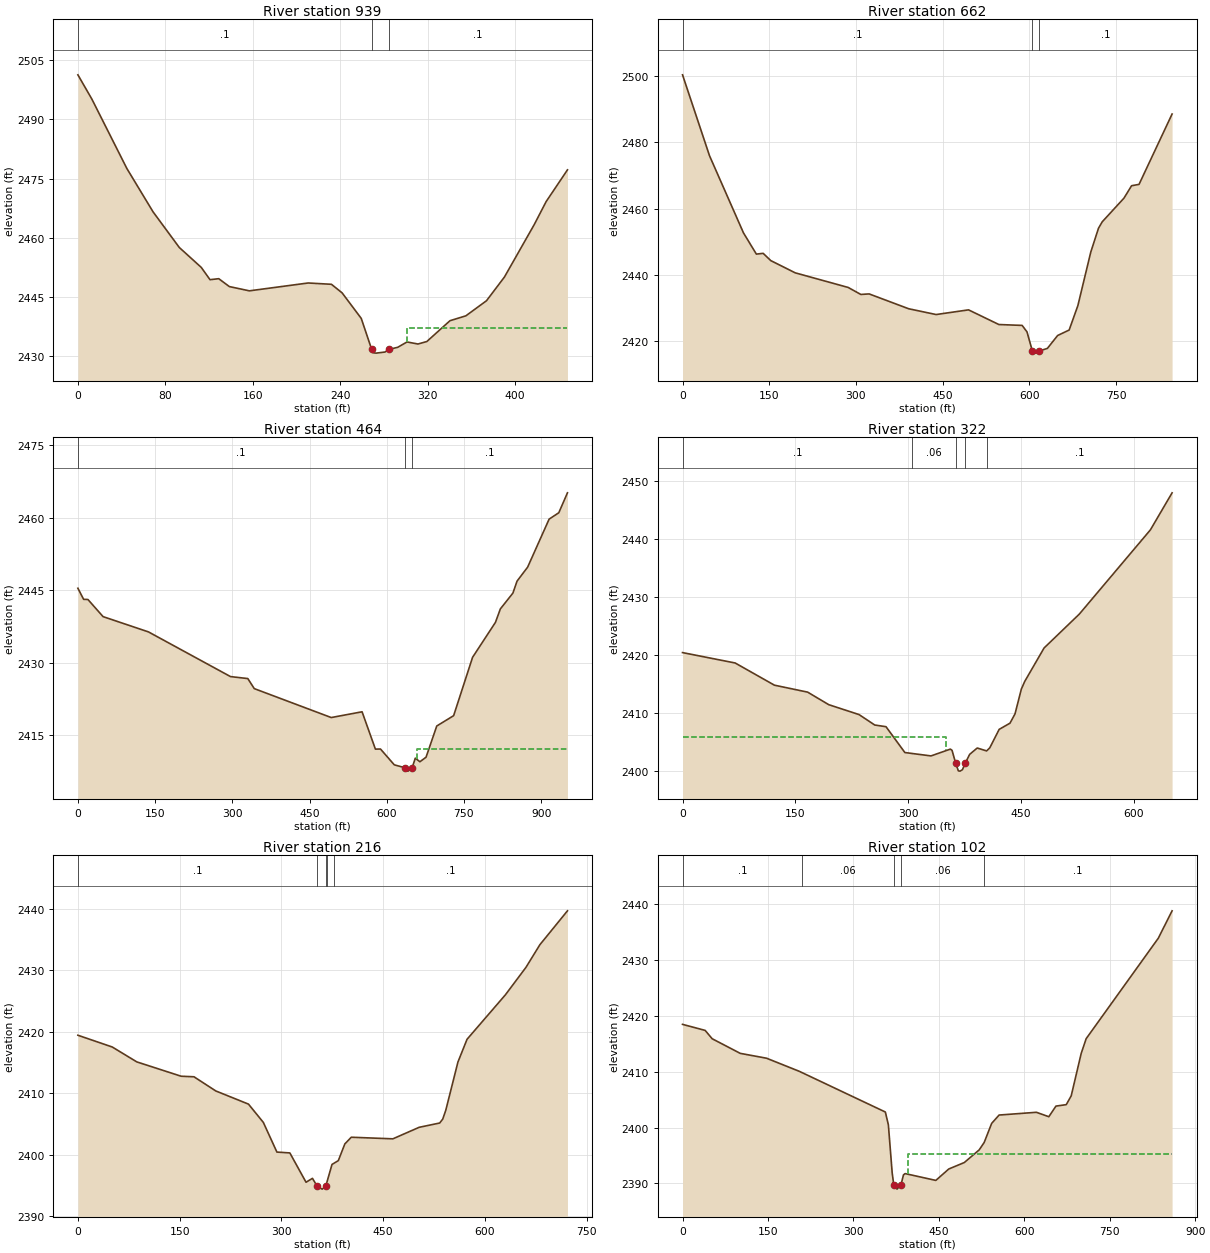
Type RM Length L Ch R = 1 ,939     ,279.2,277.1,273.4
XS GIS Cut Line= 3
2297375.02149561647604.3876004612297369.70570286647764.924541395
2297565.32687592647975.429934144
#Sta/Elev= 30
       0 2501.32    12.8 2495.16    44.8 2477.58    68.8 2466.58    92.8 2457.55
   112.9  2452.5   120.9 2449.39   128.9 2449.64   138.6 2447.64   156.9 2446.56
   210.7 2448.55     232 2448.22   241.8 2446.04   259.3 2439.57  268.87 2431.69
   270.1 2430.86   272.9 2430.77   281.1 2431.05   284.3 2431.69   292.7 2432.25
   301.2  2433.6   311.2 2433.08   319.3 2433.71   340.5 2438.99     355 2440.22
   373.9 2444.05   390.3 2450.05   417.6 2463.36   428.5 2469.19447.9926 2477.23
#Mann= 3 ,-1,0
       0      .1       0  268.87    .045       0   284.3      .1       0
#XS Ineff= 2 , 0
                           301.3         2437.04
Permanent Ineff=
       F       F
Bank Sta=268.87,284.3
XS Rating Curve= 0 ,0
Exp/Cntr(USF)=0,0
Exp/Cntr=0.3,0.1

Type RM Length L Ch R = 1 ,662     ,197,198.4,196.3
XS GIS Cut Line= 4
2297337.21163349647610.241211104 2297185.7022228648021.828273299
2297498.44357321648167.6662087222297559.20937964648150.651782923
#Sta/Elev= 30
       0 2500.27    46.7 2475.89   105.4 2452.68   127.7 2446.28   139.5 2446.51
   152.6 2444.33   194.9 2440.64   286.5 2436.24   308.4 2434.13   322.8 2434.29
     391 2429.83   438.6 2428.08   494.7 2429.49   547.2 2425.07   587.4 2424.81
   595.8 2422.86  605.08 2417.11     609 2416.46   616.9 2417.09   631.1 2417.89
   648.8 2421.77   668.7 2423.41   683.8 2430.77   706.1 2446.88   719.4 2454.04
   725.9    2456   763.5 2463.13   776.7 2466.87   789.6 2467.28846.7641 2488.47
#Mann= 3 ,-1,0
       0      .1       0  605.08    .045       0   616.9      .1       0
Bank Sta=605.08,616.9
XS Rating Curve= 0 ,0
Exp/Cntr(USF)=0,0
Exp/Cntr=0.3,0.1

Type RM Length L Ch R = 1 ,464     ,142.6,141.8,140
XS GIS Cut Line= 4
2297231.65417584647702.5552238632297082.61540782648171.677252076
2297340.68253635 648300.710816342297508.72624794648272.703531073
#Sta/Elev= 30
       0 2445.39    11.1  2443.1    19.5 2443.06    48.9 2439.52   137.1 2436.36
   296.5 2427.12   330.1 2426.71   342.7 2424.63   492.2 2418.65   552.1 2419.84
     578 2412.12   587.9 2412.14   614.7 2408.87  634.71 2408.29   641.6 2407.57
   649.5 2408.29   655.5 2410.25   664.5 2409.51   676.4 2410.45   697.2  2416.9
     730 2419.04   766.8 2431.11   811.2 2438.33   820.8 2441.12   845.1 2444.38
   853.2 2446.86   873.8 2449.76   915.5 2459.68   934.3    2461951.1171 2465.12
#Mann= 3 ,-1,0
       0      .1       0  634.71    .045       0   649.5      .1       0
#XS Ineff= 2 , 0
                          658.56         2412.14
Permanent Ineff=
       F       F
Bank Sta=634.71,649.5
XS Rating Curve= 0 ,0
Exp/Cntr(USF)=0,0
Exp/Cntr=0.3,0.1

Type RM Length L Ch R = 1 ,322     ,99.5,106.2,109.2
XS GIS Cut Line= 4
2297077.12719922648079.4633083482297053.79312956648333.950505661
2297225.88189336648386.4521624142297427.13824424648309.158056639
#Sta/Elev= 30
       0 2420.46      70 2418.67   122.2 2414.85   166.4 2413.65   194.5 2411.49
   234.7 2409.79   255.6 2407.99   270.6  2407.7   295.7 2403.25   330.5 2402.67
   356.2 2403.84   358.4 2403.64  363.12 2401.48   366.8  2400.1     369 2400.05
   372.2 2400.29   376.3 2401.49   381.8 2402.93   391.9 2404.03   404.4 2403.53
   408.6 2404.06   421.1 2407.24   435.5 2408.31   442.2 2409.92   450.6 2414.18
   455.1  2415.5   480.8 2421.25   527.7 2427.09   622.2 2441.59651.0627 2447.97
#Mann= 5 ,-1,0
       0      .1       0  305.55     .06       0  363.12    .045       0
   376.3     .06       0  405.55      .1       0
#XS Ineff= 2 , 0
          350.99  2405.9
Permanent Ineff=
       F       F
Bank Sta=363.12,376.3
XS Rating Curve= 0 ,0
Exp/Cntr(USF)=0,0
Exp/Cntr=0.3,0.1

Type RM Length L Ch R = 1 ,216     ,113.9,113.6,112.3
XS GIS Cut Line= 4
 2297058.8974573648086.7552051192297036.02191668648342.540863198
2297121.23981313648474.156238353 2297396.5122778648336.138074693
#Sta/Elev= 30
       0 2419.43    50.6 2417.52    86.8  2415.1   152.2 2412.77   171.1 2412.68
   203.2 2410.38   251.4 2408.24   273.3 2405.27   293.3 2400.45   312.4 2400.31
   336.2 2395.55   345.7 2396.18   352.8 2394.87     360 2394.43  365.25 2394.88
   374.5 2398.44   383.8 2399.06   393.4 2401.77   402.9 2402.86   464.2  2402.6
   502.9 2404.47   533.2 2405.17   537.7 2405.81   542.2 2407.25   560.1 2415.08
   573.5 2418.77     630 2425.99   660.3 2430.45   680.9 2434.14   721.5 2439.64
#Mann= 5 ,-1,0
       0      .1       0   352.8    .045       0  365.25      .1       0
  366.81     .06       0  376.81      .1       0
Bank Sta=352.8,365.25
XS Rating Curve= 0 ,0
Exp/Cntr(USF)=0,0
Exp/Cntr=0.3,0.1

Type RM Length L Ch R = 1 ,102     ,42.9,43.8,44.4
XS GIS Cut Line= 4
2297049.41799149648094.7762915672296963.60287412648428.217288695
2297045.27884109648523.2691610872297402.34579522648366.764041132
#Sta/Elev= 30
       0 2418.48    39.7  2417.4      52 2415.91   101.3 2413.29   147.5 2412.42
   204.9 2410.08   356.1 2402.79   361.4 2400.49   368.1 2391.87   370.9 2389.74
   376.6 2388.99  383.51 2389.76   387.9 2391.54   390.8 2391.77   444.7 2390.55
   467.4 2392.59   494.7 2393.75   520.8 2396.01   529.6 2397.34   542.7 2400.75
   555.8 2402.25   621.3 2402.74   643.1 2401.95   655.6 2403.85   673.7 2404.11
   682.4 2405.69   699.9 2413.27   708.6 2415.91   835.3  2433.9   859.5  2438.8
#Mann= 5 ,-1,0
       0      .1       0     210     .06       0   370.9    .045       0
  383.51     .06       0  529.63      .1       0
#XS Ineff= 2 , 0
                           395.7         2395.23
Permanent Ineff=
       F       F
Bank Sta=370.9,383.51
XS Rating Curve= 0 ,0
Exp/Cntr(USF)=0,0
Exp/Cntr=0.3,0.1

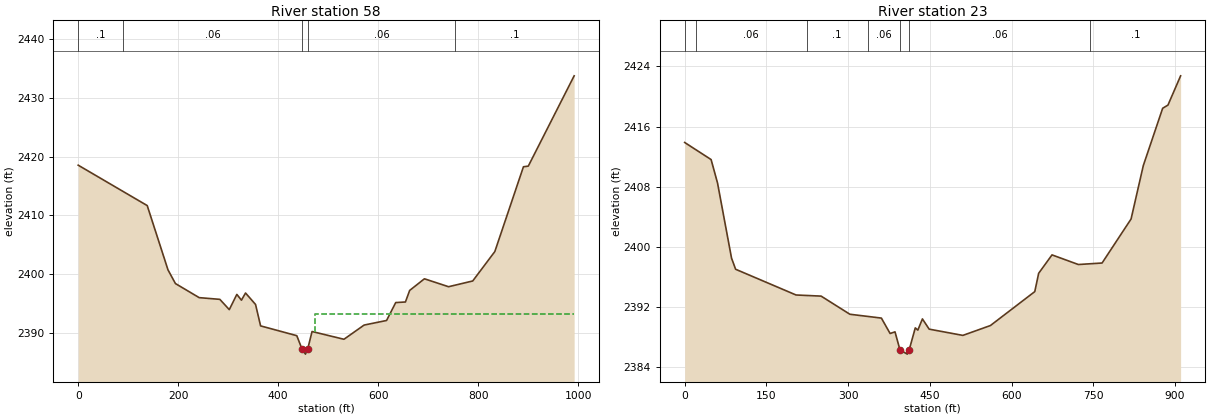
Type RM Length L Ch R = 1 ,58      ,36.2,35.8,35.9
XS GIS Cut Line= 6
2297039.64803613648072.8345749462296940.29119139648222.326460836
2296902.77226395648366.1996871992296990.48284426648527.268207408
2297109.71848188648588.5507662522297389.11479857648399.464591079
#Sta/Elev= 30
       0 2418.56     138 2411.68   179.5 2400.74   194.4  2398.4   241.9    2396
   283.2 2395.71   302.1 2393.96   317.2 2396.55   326.4 2395.57   334.6 2396.79
   354.6 2394.84   364.7 2391.19   437.1 2389.52  447.48 2387.25   454.4 2386.38
   458.9 2387.25   467.6 2390.23   531.4 2388.91   571.7 2391.33   616.6 2392.11
   634.9 2395.16   654.3 2395.26   662.8 2397.23   692.3 2399.21   740.6 2397.86
   788.9 2398.84   833.1 2403.85   890.3 2418.29     900  2418.4   991.7 2433.78
#Mann= 5 ,-1,0
       0      .1       0      90     .06       0  447.48    .045       0
   458.9     .06       0   754.3      .1       0
#XS Ineff= 2 , 0
                          472.58         2393.27
Permanent Ineff=
       F       F
Bank Sta=447.48,458.9
XS Rating Curve= 0 ,0
Exp/Cntr(USF)=0,0
Exp/Cntr=0.3,0.1

Type RM Length L Ch R = 1 ,23      ,,,
XS GIS Cut Line= 6
2296985.97848958648134.1525341312296877.32922769648372.597558549
2296905.35049215648479.4171610352296997.96808074648576.297483834
2297094.84840354648604.9740593832297339.37433829648438.727425459
#Sta/Elev= 30
       0 2413.88    48.5 2411.61    60.3 2408.49      86 2398.51    93.5 2397.03
   204.4 2393.61   250.4 2393.46   303.2 2391.05     361 2390.54     377 2388.49
     386 2388.71   395.1 2386.31   408.5 2385.75  411.95  2386.3   423.2 2389.24
   427.9 2388.94   436.3 2390.43   448.7 2389.07   510.5 2388.24   561.1 2389.55
   642.5 2394.06   649.6 2396.49   674.1 2398.94   722.5 2397.66     766 2397.86
   819.2 2403.71   841.7 2410.82   877.2 2418.43   886.9 2418.85910.1289 2422.74
#Mann= 7 ,-1,0
       0      .1       0      20     .06       0  224.03      .1       0
  335.56     .06       0   395.1    .045       0  411.95     .06       0
  744.44      .1       0
Bank Sta=395.1,411.95
XS Rating Curve= 0 ,0
Exp/Cntr(USF)=0,0
Exp/Cntr=0.3,0.1
LCMann Table=0

Chan Stop Cuts=-1
Use User Specified Reach Order=0
Composite Channel Slope=5